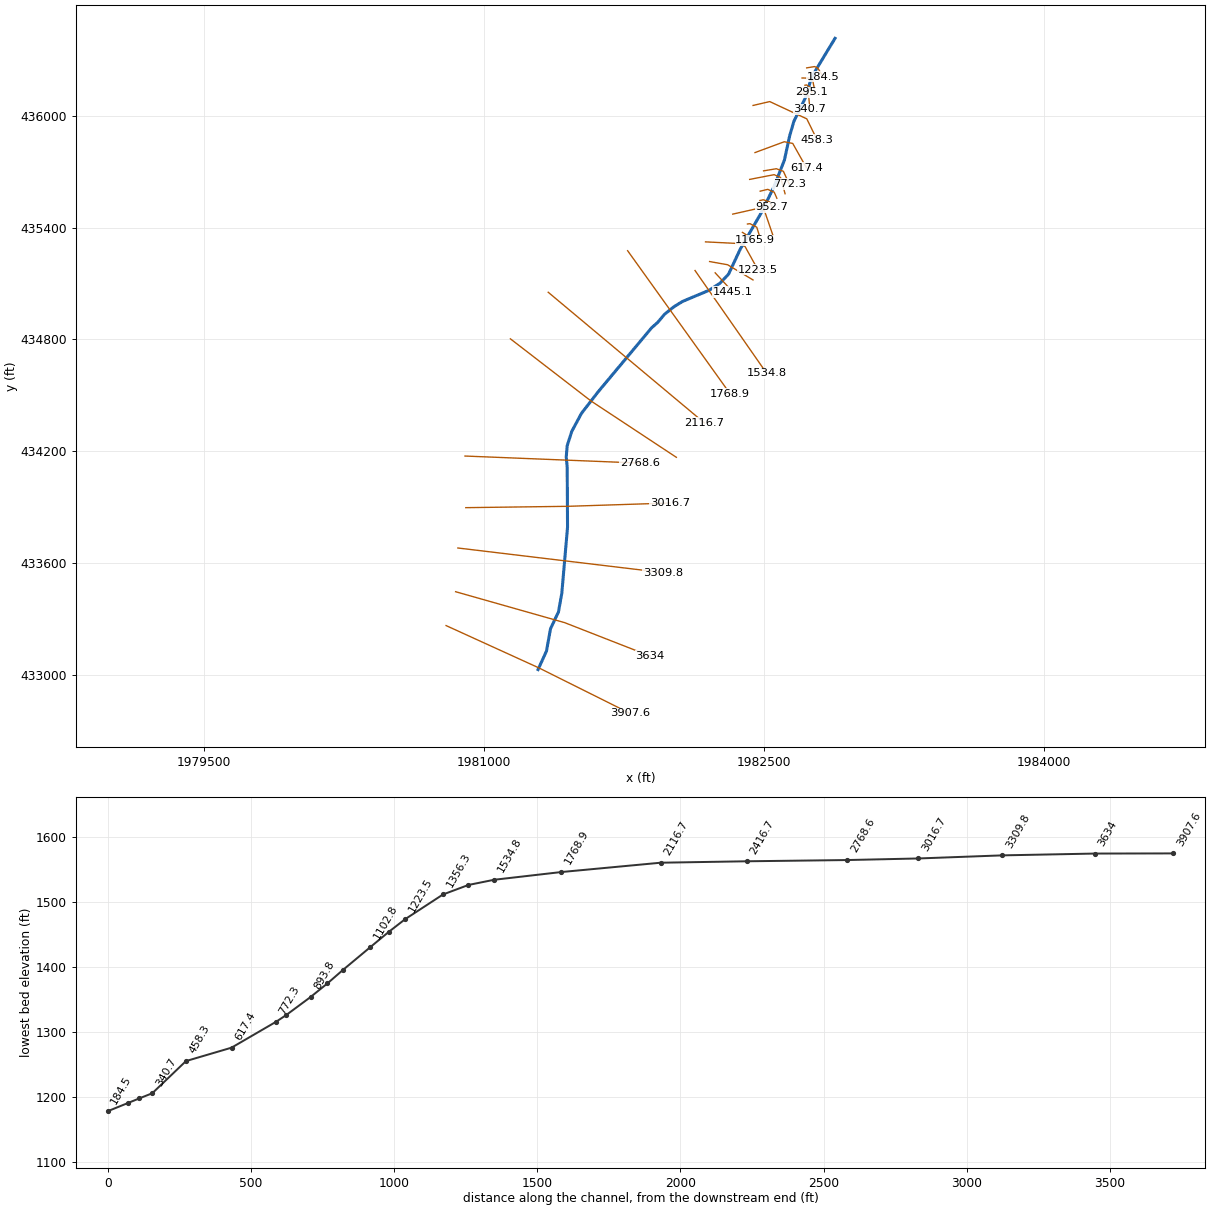
--- StationBrh.prj (project) ---

Proj Title=StationBrh
Current Plan=p01
Default Exp/Contr=0,0
English Units
Geom File=g01
Flow File=f01
Plan File=p01
BEGIN DESCRIPTION:
END DESCRIPTION:
DSS Export Rating Curves= 0
DSS Export Rating Curve Sorted= 0
DSS Export Volume Flow Curves= 0
DXF OffsetX= 0
DXF OffsetY= 0
DXF ScaleX= 0
DXF ScaleY= 0

--- StationBrh.p01 (plan) ---

Plan Title=Floodplain
Program Version=4.00
Geom File=g01
Flow File=f01
K Sum by GR=0
Std Step Tol=0.01
Critical Tol=0.01
Num of Std Step Trials=20
Max Error Tol=0.3
Flow Tol Ratio=0.001
Split Flow NTrial=30
Split Flow Tol=0.02
Split Flow Ratio=0.02
Log Output Level=0
Friction Slope Method=1
Unsteady Friction Slope Method=2
Unsteady Bridges Friction Slope Method=1
Global Log Level=0
CheckData=False
Run HTab=0
Run UNet=0
Run PostProcess=0
UNET Theta=0
UNET Theta Warmup=0
UNET ZTol=0
UNET ZSATol=0
UNET MxIter=0
UNET MaxInSteps=0
UNET DtIC=0
UNET DtMin=0
UNET MaxCRTS=0
UNET WFStab=0
UNET SFStab=0
UNET WFX=0
UNET SFX=0
UNET DSS MLevel=0
UNET DZMax Abort=0
UNET Convert EG Bridges=0
UNET Use Existing IB Tables=0
UNET Froude Limit=0
UNET Froude Power=0
Write IC File=0
Echo Input=False
Echo Output=False
Write Detailed=0

--- StationBrh.f01 (steady flow) ---

Flow Title=NFF Regression Equation
Program Version=4.00
Number of Profiles=1
Profile Names=P100yr
River Rch & RM=StationBrh,Main      ,3907.6
366.0244
River Rch & RM=StationBrh,Main      ,3634
366.0244
River Rch & RM=StationBrh,Main      ,3309.8
549.5786
River Rch & RM=StationBrh,Main      ,295.1
589.3573
Boundary for River Rch & Prof#=StationBrh,Main      ,1
Up Type=0
Dn Type=3
Dn Slope=0.171044

--- StationBrh.g01 (geometry) ---

Geom Title=USGS 3m DEM
Program Version=4.10

River Reach=StationBrh      ,Main
Reach XY= 30
     1981290.487      433028.361     1981335.626       433127.32
     1981357.439      433247.693     1981399.863      433337.389
     1981417.821      433437.975     1981448.474       433792.25
     1981446.737      434113.431     1981441.529      434168.986
     1981446.737       434229.75     1981471.043      434306.139
     1981523.126      434403.362     1981611.668      434517.945
     1981898.126      434861.695     1981931.112      434891.209
     1981967.571      434934.611     1982019.654      434976.278
     1982064.793      435004.056     1982205.418      435063.084
     1982264.446      435101.278     1982311.014      435150.616
     1982373.821      435285.306     1982484.932      435478.014
     1982556.113      435623.848     1982609.932      435762.736
      1982637.71      435891.209     1982660.279      435969.334
     1982724.515      436101.278     1982748.821      436184.612
     1982769.654      436231.487     1982880.922      436415.764

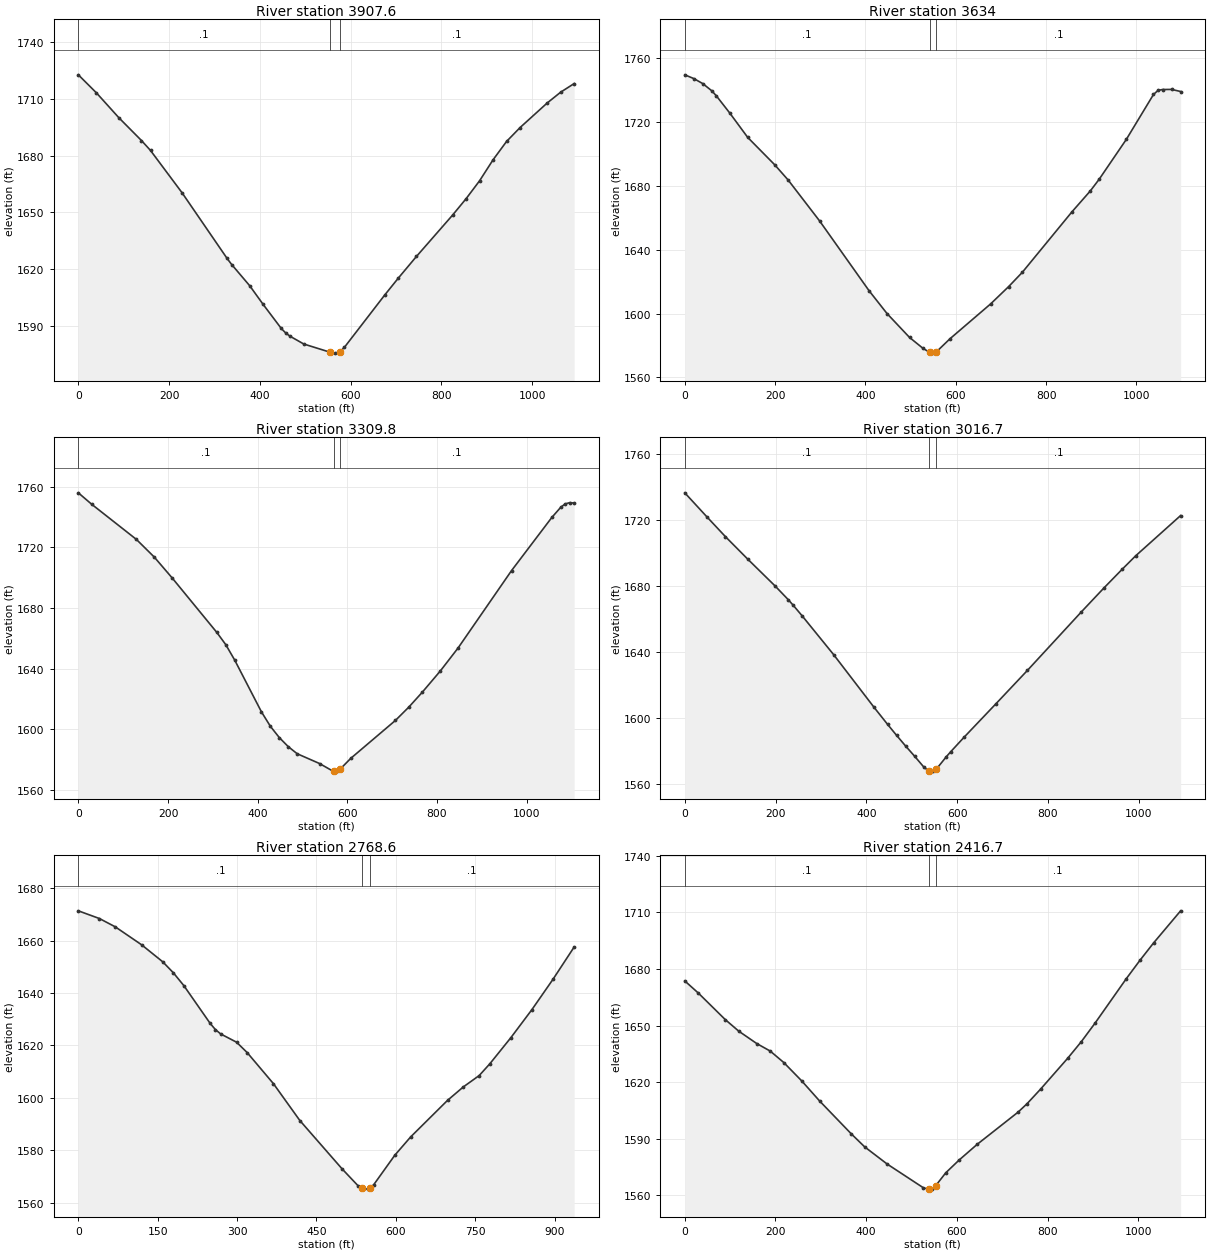
Type RM Length L Ch R = 1 ,3907.6  ,269.9,273.4,277.7
XS GIS Cut Line= 3
     1980797.964       433264.37      1981294.96      433037.306
     1981783.252      432793.159
#Sta/Elev= 30
       0 1722.76    39.7 1713.26    89.4 1700.02   139.1 1687.98     159 1682.73
   228.5 1660.34   327.8 1625.55   337.8 1622.36   377.5 1611.13   407.3 1601.19
   447.1  1588.5     457 1586.08   466.9 1584.32   496.7 1580.27   553.9 1575.98
   566.3 1575.45   576.2 1576.23   586.1  1578.5   675.4 1606.34   705.2 1615.24
   744.9 1626.63   824.3 1648.46   854.1 1657.15   883.9 1666.66   913.7  1677.8
   943.4  1687.5   973.2 1694.86  1032.8 1707.83  1062.6 1713.58  1092.3 1718.13
#Mann= 3 , 0 , 0
       0      .1       0   553.9    .045       0   576.2      .1       0
Bank Sta=553.9,576.2
XS Rating Curve= 0 ,0
Exp/Cntr=0.3,0.1

Type RM Length L Ch R = 1 ,3634    ,320.6,324.1,327.6
XS GIS Cut Line= 3
     1980849.082      433446.072     1981433.029      433280.102
      1981890.01      433101.026
#Sta/Elev= 30
       0 1749.43    19.9 1747.09    39.8 1743.94    59.7 1739.44    69.7 1736.34
    99.5 1725.54   139.3 1710.26     199 1693.15   228.9 1683.57   298.6 1657.93
     408 1614.29   447.8 1599.99   497.6 1585.05   527.5  1578.2     542 1575.73
   547.4 1575.22     557    1576   587.2 1584.22   677.2 1606.03   717.3 1616.92
   747.3 1625.78   857.5 1663.74   897.6 1676.64   917.6 1684.08   977.7 1709.03
  1037.8 1737.12  1047.8 1739.67  1057.8 1740.23  1077.9  1740.3  1097.9 1738.99
#Mann= 3 , 0 , 0
       0      .1       0     542    .045       0     557      .1       0
Bank Sta=542,557
XS Rating Curve= 0 ,0
Exp/Cntr=0.3,0.1

Type RM Length L Ch R = 1 ,3309.8  ,290,293,296.4
XS GIS Cut Line= 2
      1980861.28      433680.703     1981959.152      433548.767
#Sta/Elev= 30
       0 1756.07    29.9  1748.5   129.5 1725.33   169.4 1713.66   209.2 1699.93
   308.8 1663.98   328.7 1655.94   348.7 1645.73   408.4 1611.53   428.4 1601.97
   448.3 1594.54   468.2 1588.58   488.1  1583.9   537.9 1577.45   567.8 1572.43
   569.3 1572.45   577.8 1572.58   584.3 1573.87   607.7 1580.89   707.3 1605.91
   737.2 1614.72   767.1  1624.5   806.9 1638.36   846.8 1653.64   966.3 1704.81
    1056 1739.82  1075.9 1746.54  1085.8 1748.77  1095.8 1749.57  1105.8  1749.3
#Mann= 3 , 0 , 0
       0      .1       0   569.3    .045       0   584.3      .1       0
Bank Sta=569.3,584.3
XS Rating Curve= 0 ,0
Exp/Cntr=0.3,0.1

Type RM Length L Ch R = 1 ,3016.7  ,249.3,248,246.4
XS GIS Cut Line= 3
     1980903.714      433897.123     1981449.786      433904.344
     1981995.481      433921.949
#Sta/Elev= 30
       0 1736.53    49.6 1721.68    89.4 1709.97     139  1696.2   198.6  1680.1
   228.4 1671.55   238.3 1668.46   258.2 1661.98   327.7  1638.4     417 1606.32
   446.8 1595.99   466.7  1589.3   486.5 1582.86   506.4 1576.65   526.3 1570.19
   536.2 1567.98   538.6  1567.9   546.1 1567.67   553.6  1569.1     556 1569.56
   575.9 1576.36   585.8 1579.46   615.6 1588.37   685.1 1608.48   754.6 1628.77
   873.7 1664.36   923.3 1678.84     963 1690.05   992.8 1698.24  1092.1 1722.75
#Mann= 3 , 0 , 0
       0      .1       0   538.6    .045       0   553.6      .1       0
Bank Sta=538.6,553.6
XS Rating Curve= 0 ,0
Exp/Cntr=0.3,0.1

Type RM Length L Ch R = 1 ,2768.6  ,365.9,352,339.7
XS GIS Cut Line= 2
     1980899.511      434174.143     1981835.711      434136.346
#Sta/Elev= 30
       0 1671.33    39.9 1668.39    69.8 1665.23   119.6 1658.38   159.5  1651.9
   179.4 1647.75   199.4 1642.82   249.2  1628.4   259.2 1626.02   269.1 1624.39
     299 1621.25     319 1617.31   368.8 1605.42   418.6  1591.4   498.4 1572.97
   528.3 1566.59   536.5 1565.49   548.2 1565.24   551.5 1565.79   558.2 1566.92
   598.1 1578.17     628 1585.14   697.7 1599.08   727.6 1604.21   757.5 1608.53
   777.5 1612.98   817.4 1622.98   857.2 1633.68   897.1 1645.26     937 1657.54
#Mann= 3 , 0 , 0
       0      .1       0   536.5    .045       0   551.5      .1       0
Bank Sta=536.5,551.5
XS Rating Curve= 0 ,0
Exp/Cntr=0.3,0.1

Type RM Length L Ch R = 1 ,2416.7  ,300.9,299.9,297.4
XS GIS Cut Line= 3
     1981142.482      434803.175     1981574.257       434469.53
     1982031.274       434167.31
#Sta/Elev= 30
       0 1673.71    29.8 1667.29    89.3  1653.2     119 1647.08   158.7 1640.51
   188.5 1636.51   218.3 1630.45     258 1620.68   297.6 1609.99   367.1 1592.65
   396.8 1585.71   446.4 1576.61   525.8 1564.09   535.7 1563.32   538.2 1563.36
   545.7  1563.5   553.2 1565.08   575.6 1571.98   605.4 1578.82   645.3 1587.15
   734.9  1604.1   754.9 1608.61   784.8 1616.36   844.5  1632.7   874.4 1641.45
   904.3 1651.15     974 1674.98  1003.9 1684.64  1033.8 1693.81  1093.6 1710.88
#Mann= 3 , 0 , 0
       0      .1       0   538.2    .045       0   553.2      .1       0
Bank Sta=538.2,553.2
XS Rating Curve= 0 ,0
Exp/Cntr=0.3,0.1

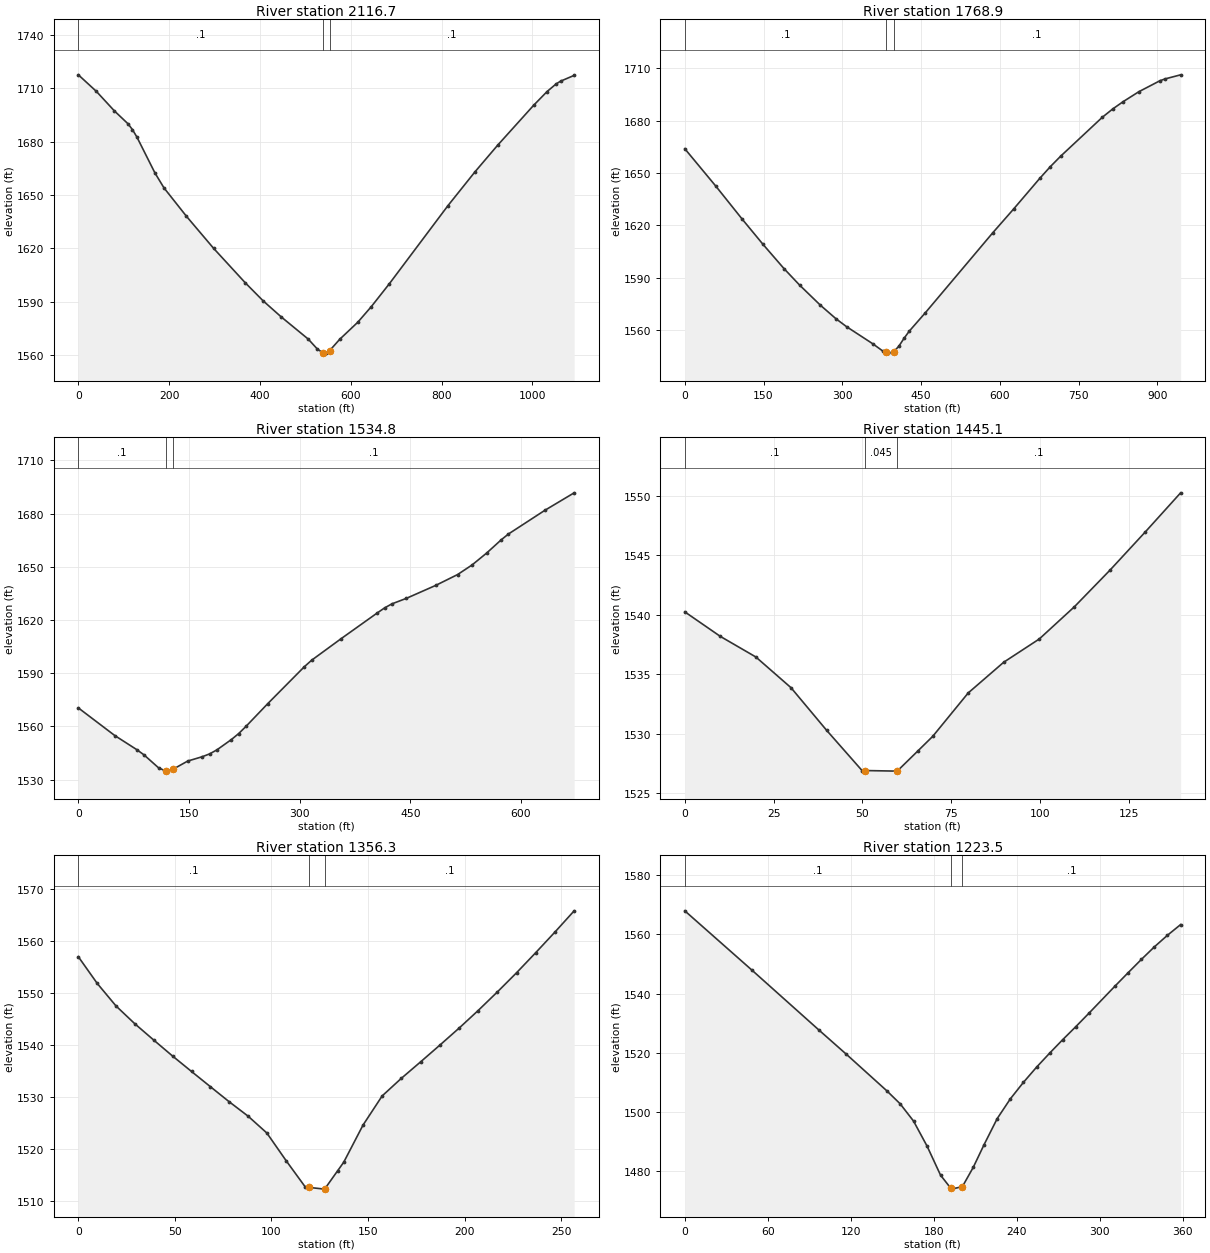
Type RM Length L Ch R = 1 ,2116.7  ,353.5,347.8,342.1
XS GIS Cut Line= 3
     1981344.984      435053.085     1981763.422      434702.335
      1982181.86      434351.584
#Sta/Elev= 30
       0 1717.62    39.7 1708.32    79.4 1697.34   109.2 1690.14   119.1 1686.84
     129 1682.64   168.8 1662.41   188.6 1654.06   238.2 1638.05   297.8 1620.09
   367.3 1600.78     407 1590.53   446.7 1581.53   506.3 1569.03   526.2 1563.49
   538.5 1561.28     546 1561.13   553.5 1562.55   575.8 1568.94   615.5 1578.51
   645.3 1587.29     685 1600.15     814 1644.05   873.6 1663.08   923.2 1677.95
  1002.6 1700.44  1032.4 1708.23  1052.3 1712.51  1062.2 1714.06    1092 1717.31
#Mann= 3 , 0 , 0
       0      .1       0   538.5    .045       0   553.5      .1       0
Bank Sta=538.5,553.5
XS Rating Curve= 0 ,0
Exp/Cntr=0.3,0.1

Type RM Length L Ch R = 1 ,1768.9  ,234.3,234.1,233.8
XS GIS Cut Line= 2
     1981770.293      435276.067     1982319.441       434507.91
#Sta/Elev= 30
       0 1663.84    59.6 1642.21   109.3  1623.5   149.1    1609   188.8  1595.2
   218.7 1585.69   258.4 1574.14   288.2 1566.36   308.1 1561.88   357.8 1552.13
   377.7 1547.79   382.9 1547.23   387.6 1546.73   397.9 1547.58   407.5 1550.62
   417.5 1555.19   427.4 1559.29   457.2 1569.54   586.4 1615.64   626.2 1629.29
   675.9 1646.81   695.8 1653.45   715.6  1659.5   795.2 1681.87     815 1686.63
   834.9 1690.82   864.7  1696.5   904.5 1702.73   914.4 1703.82   944.3 1706.18
#Mann= 3 , 0 , 0
       0      .1       0   382.9    .045       0   397.9      .1       0
Bank Sta=382.9,397.9
XS Rating Curve= 0 ,0
Exp/Cntr=0.3,0.1

Type RM Length L Ch R = 1 ,1534.8  ,86.6,89.7,92.9
XS GIS Cut Line= 2
     1982131.279      435169.698     1982514.987      434618.027
#Sta/Elev= 30
       0 1570.48    49.4  1554.9    79.1 1546.98    88.9 1544.04   108.7 1536.72
   118.6 1534.84   128.5 1535.94   148.2 1540.51     168 1542.97   177.9 1544.55
   187.8 1546.82   207.5 1552.65   217.4 1556.04   227.3 1560.09   256.9 1572.95
   306.4 1593.72   316.2 1597.35   355.8 1609.39   405.2 1624.02     415 1626.82
   424.9  1629.1   444.7 1632.25   484.2  1639.5   513.9 1645.61   533.6 1651.04
   553.4 1657.76   573.2 1665.24     583 1668.52   632.5 1681.91     672 1691.71
#Mann= 3 , 0 , 0
       0      .1       0   118.6    .045       0   128.5      .1       0
Bank Sta=118.6,128.5
XS Rating Curve= 0 ,0
Exp/Cntr=0.3,0.1

Type RM Length L Ch R = 1 ,1445.1  ,82.4,88.9,95.3
XS GIS Cut Line= 2
     1982239.142      435157.225     1982333.998      435054.738
#Sta/Elev= 17
       0 1540.24      10 1538.18      20 1536.45    29.9 1533.87    39.9  1530.3
    49.9 1526.91    50.6 1526.91    59.8 1526.86    65.6 1528.55    69.8 1529.78
    79.8 1533.43    89.8 1536.01    99.8 1537.96   109.7 1540.67   119.7 1543.74
   129.7 1546.97   139.6 1550.24
#Mann= 3 , 0 , 0
       0      .1       0    50.6    .045       0    59.8      .1       0
Bank Sta=50.6,59.8
XS Rating Curve= 0 ,0
Exp/Cntr=0.3,0.1

Type RM Length L Ch R = 1 ,1356.3  ,128.7,132.6,129
XS GIS Cut Line= 3
     1982209.318      435217.918     1982305.446      435200.777
     1982441.914      435119.065
#Sta/Elev= 29
       0 1556.96     9.8 1551.81    19.5 1547.48    29.3 1544.03    39.1 1540.89
    48.8 1537.83    58.6 1534.86    68.4 1531.92    78.1 1529.03    87.9 1526.25
    97.6 1523.01   107.6 1517.67   117.5 1512.61   119.2 1512.54   127.5  1512.2
   134.2 1515.71   137.4 1517.38   147.4 1524.54   157.3 1530.15   167.2 1533.53
   177.2 1536.71   187.1 1539.91   197.1  1543.2     207  1546.6   216.9 1550.16
   226.9 1553.88   236.8 1557.74   246.8 1561.73   256.7  1565.8
#Mann= 3 , 0 , 0
       0      .1       0   119.2    .045       0   127.5      .1       0
Bank Sta=119.2,127.5
XS Rating Curve= 0 ,0
Exp/Cntr=0.3,0.1

Type RM Length L Ch R = 1 ,1223.5  ,61.9,57.5,60.7
XS GIS Cut Line= 4
      1982187.49      435323.495     1982372.162      435314.267
     1982399.279      435298.146     1982467.968      435173.852
#Sta/Elev= 28
       0 1567.94    48.7 1547.86    97.3 1527.58   116.8 1519.54     146 1507.23
   155.7 1502.82   165.4 1496.98   175.2 1488.51   184.9 1478.75   192.2 1474.38
   192.8 1474.02   200.7 1474.86   208.6 1481.41   216.4 1489.04   225.9 1497.84
   235.4  1504.5   244.8 1510.03   254.3 1515.16   263.8 1519.91   273.2 1524.44
   282.7 1528.84   292.2 1533.38   311.1 1542.56   320.6 1547.08   330.1 1551.53
   339.5 1555.77     349  1559.7   358.5  1563.3
#Mann= 3 , 0 , 0
       0      .1       0   192.2    .045       0   200.7      .1       0
Bank Sta=192.2,200.7
XS Rating Curve= 0 ,0
Exp/Cntr=0.3,0.1

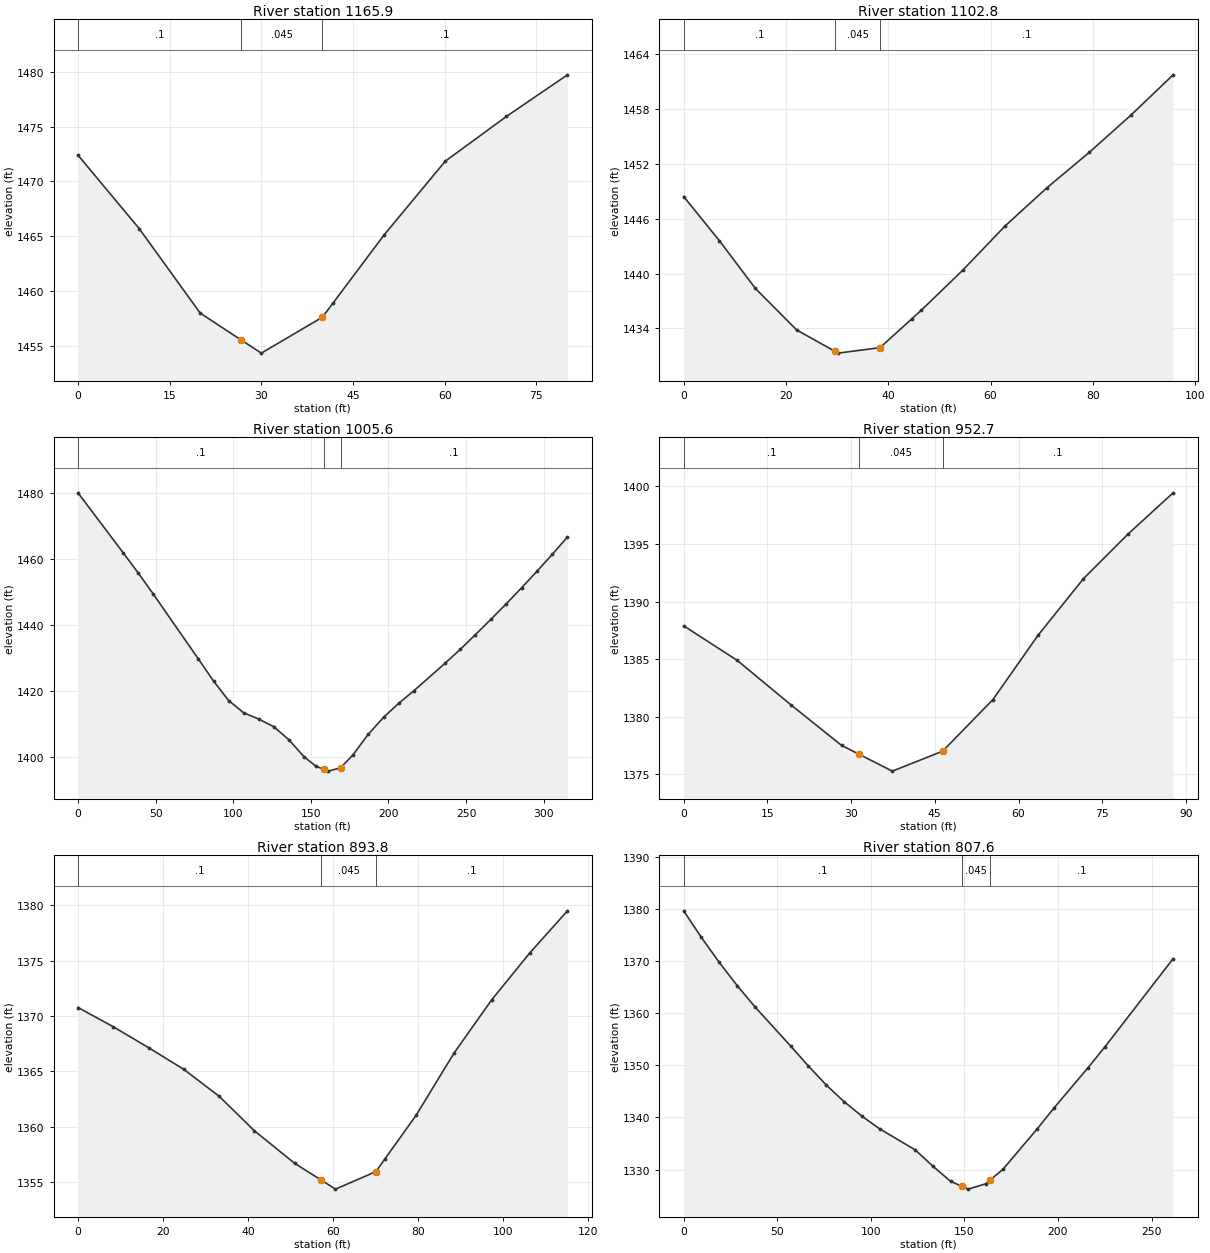
Type RM Length L Ch R = 1 ,1165.9  ,61.4,63.1,59.6
XS GIS Cut Line= 2
     1982384.969      435374.421      1982452.84        435331.9
#Sta/Elev= 11
       0 1472.39      10  1465.7      20 1457.98    26.7 1455.53      30 1454.33
      40 1457.61    41.7 1458.87    50.1 1465.12    60.1 1471.84    70.1 1475.92
    80.1 1479.72
#Mann= 3 , 0 , 0
       0      .1       0    26.7    .045       0      40      .1       0
Bank Sta=26.7,40
XS Rating Curve= 0 ,0
Exp/Cntr=0.3,0.1

Type RM Length L Ch R = 1 ,1102.8  ,95.1,97.2,91.4
XS GIS Cut Line= 4
     1982411.954      435419.396     1982425.855      435421.031
     1982461.835      435402.224     1982474.101      435362.973
#Sta/Elev= 15
       0 1448.41       7 1443.58      14 1438.39    22.1 1433.84    29.6  1431.5
    30.2 1431.31    38.4 1431.91    44.6 1435.05    46.5 1436.01    54.6 1440.38
    62.8 1445.17      71 1449.35    79.3 1453.23    87.5 1457.32    95.7  1461.7
#Mann= 3 , 0 , 0
       0      .1       0    29.6    .045       0    38.4      .1       0
Bank Sta=29.6,38.4
XS Rating Curve= 0 ,0
Exp/Cntr=0.3,0.1

Type RM Length L Ch R = 1 ,1005.6  ,50.1,53,60.8
XS GIS Cut Line= 4
     1982333.044       435472.32     1982475.009      435504.392
      1982503.13       435490.31     1982548.104      435359.475
#Sta/Elev= 30
       0 1479.99    29.1 1461.81    38.8 1455.68    48.5 1449.29    77.6 1429.57
    87.3 1422.91      97 1417.01   106.7 1413.29   116.4 1411.38   126.1 1409.07
   135.8 1405.13   145.5    1400   153.4 1397.04   158.2 1396.17   161.3  1395.6
   169.1 1396.62     177 1400.44   186.9 1406.74   196.8  1411.9   206.6 1416.16
   216.5 1420.03   236.3 1428.26   246.2  1432.5     256 1436.98   265.9 1441.59
   275.8 1446.31   285.7 1451.17   295.6 1456.17   305.5 1461.33   315.3  1466.6
#Mann= 3 , 0 , 0
       0      .1       0   158.2    .045       0   169.1      .1       0
Bank Sta=158.2,169.1
XS Rating Curve= 0 ,0
Exp/Cntr=0.3,0.1

Type RM Length L Ch R = 1 ,952.7   ,62.2,58.8,56.1
XS GIS Cut Line= 4
     1982478.189      435545.325     1982496.997      435549.413
     1982531.341      435537.965     1982544.425      435508.527
#Sta/Elev= 12
       0  1387.9     9.6  1384.9    19.2 1381.05    28.3 1377.52    31.4 1376.76
    37.4 1375.29    46.4 1377.02    55.4 1381.49    63.5 1387.08    71.6 1391.97
    79.6 1395.85    87.7 1399.44
#Mann= 3 , 0 , 0
       0      .1       0    31.4    .045       0    46.4      .1       0
Bank Sta=31.4,46.4
XS Rating Curve= 0 ,0
Exp/Cntr=0.3,0.1

Type RM Length L Ch R = 1 ,893.8   ,86,86.1,83
XS GIS Cut Line= 4
     1982480.097      435595.524     1982520.438      435605.336
     1982555.328      435590.072     1982569.501      435557.363
#Sta/Elev= 16
       0 1370.77     8.3 1369.03    16.6 1367.14    24.9 1365.18    33.2 1362.75
    41.5 1359.63      51 1356.68    57.2 1355.18    60.6 1354.35    70.1 1355.93
    72.2 1357.06    79.6 1361.04    88.5 1366.65    97.4 1371.48   106.3 1375.69
   115.2 1379.51
#Mann= 3 , 0 , 0
       0      .1       0    57.2    .045       0    70.1      .1       0
Bank Sta=57.2,70.1
XS Rating Curve= 0 ,0
Exp/Cntr=0.3,0.1

Type RM Length L Ch R = 1 ,807.6   ,34.2,35.3,41.7
XS GIS Cut Line= 4
     1982423.811      435658.761     1982554.646       435684.11
      1982588.99      435669.391     1982613.522      435581.895
#Sta/Elev= 24
       0  1379.6     9.5 1374.49      19 1369.72    28.6 1365.26    38.1 1361.19
    57.1  1353.7    66.6 1349.87    76.2  1346.2    85.7 1343.02    95.2 1340.24
   104.7  1337.8   123.8 1333.75   133.3 1330.58   142.6 1327.75   148.5  1326.8
     152 1326.24   161.3 1327.25   163.5 1327.91   170.6 1330.05   188.8 1337.75
   197.9 1341.82   216.1 1349.54   225.2 1353.58   261.5 1370.42
#Mann= 3 , 0 , 0
       0      .1       0   148.5    .045       0   163.5      .1       0
Bank Sta=148.5,163.5
XS Rating Curve= 0 ,0
Exp/Cntr=0.3,0.1

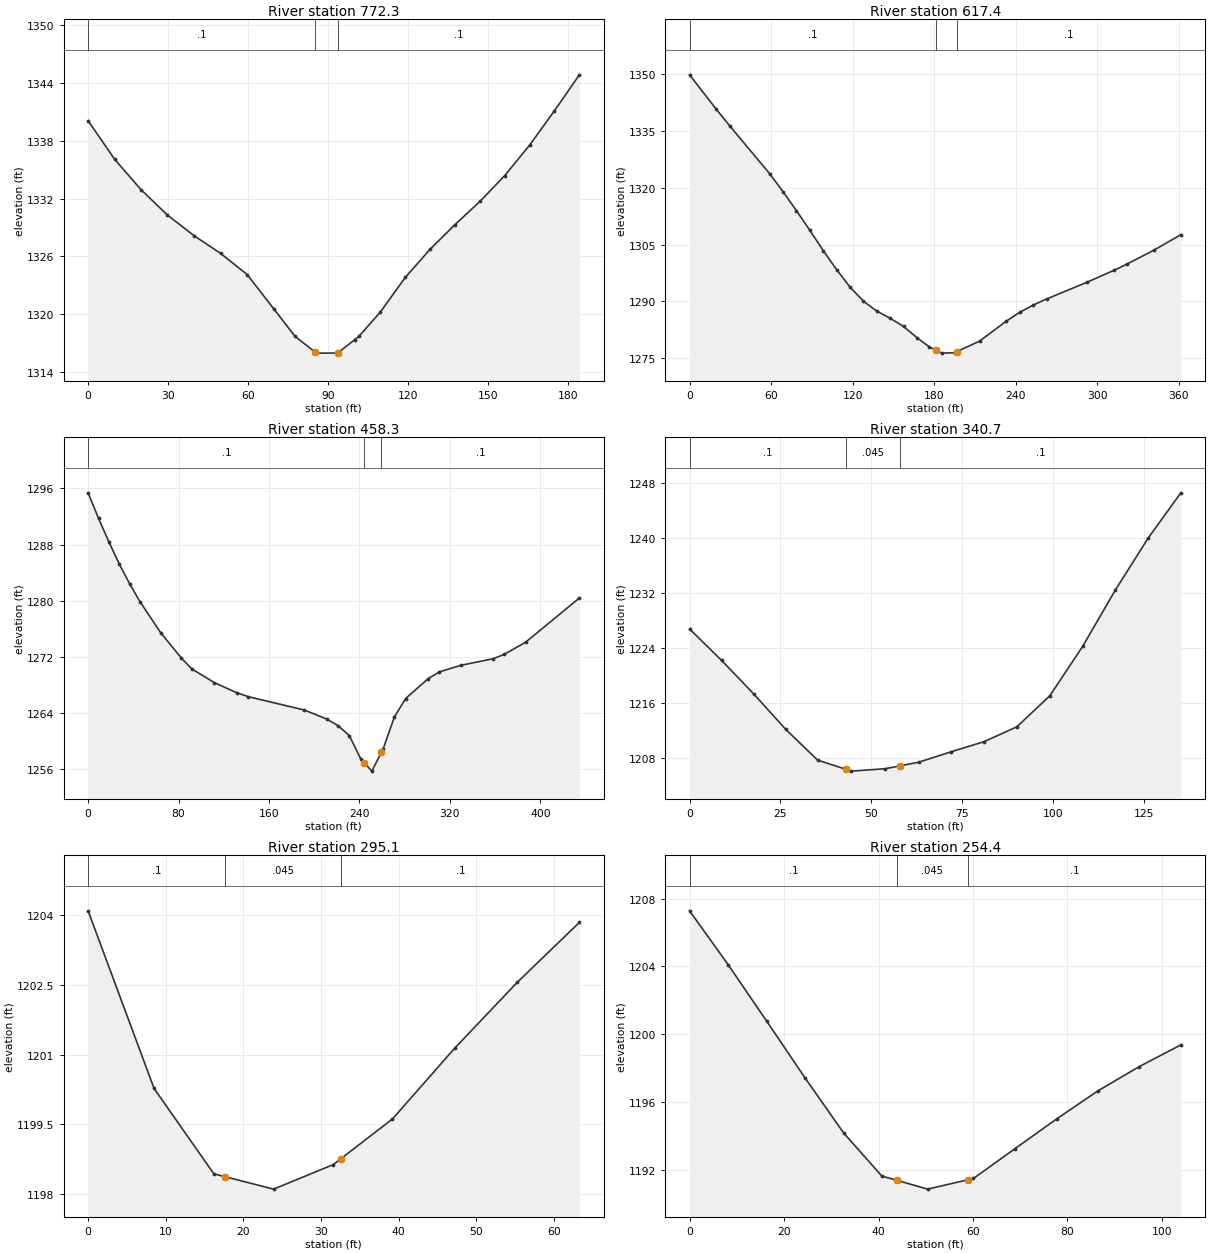
Type RM Length L Ch R = 1 ,772.3   ,150.7,154.8,163.9
XS GIS Cut Line= 4
     1982498.223      435704.553     1982566.912      435716.001
     1982604.527        435702.1     1982635.601      435634.229
#Sta/Elev= 23
       0 1340.06      10 1336.06    19.9 1332.91    29.8 1330.29    39.8 1328.15
    49.7 1326.33    59.7 1324.13    69.6 1320.61    77.7 1317.72      85 1316.14
    85.7 1315.99    93.7    1316     100 1317.37   101.7 1317.74   109.7 1320.25
   119.1 1323.85   128.4 1326.76   137.7  1329.3   147.1 1331.71   156.4 1334.39
   165.7 1337.53     175 1341.08   184.4 1344.82
#Mann= 3 , 0 , 0
       0      .1       0      85    .045       0    93.7      .1       0
Bank Sta=85,93.7
XS Rating Curve= 0 ,0
Exp/Cntr=0.3,0.1

Type RM Length L Ch R = 1 ,617.4   ,165.1,159.1,153.8
XS GIS Cut Line= 4
     1982452.431       435802.68     1982609.303      435860.915
     1982654.408      435851.743     1982727.185      435722.543
#Sta/Elev= 30
       0 1349.91    19.7 1340.79    29.5 1336.43    59.1  1323.7    68.9 1318.95
    78.7 1313.97    88.6 1308.75    98.4 1303.41   108.3 1298.36   118.1 1293.76
     128 1290.03   137.8 1287.42   147.6 1285.54   157.5 1283.36   167.3  1280.4
   176.5 1277.94   181.7 1277.01   185.7  1276.3     195 1276.42   196.7  1276.7
   213.4 1279.46   233.1 1284.75     243  1287.1   252.9 1289.01   262.8 1290.62
   292.4 1295.03   312.2 1298.18   322.1 1299.88   341.9 1303.56   361.6 1307.63
#Mann= 3 , 0 , 0
       0      .1       0   181.7    .045       0   196.7      .1       0
Bank Sta=181.7,196.7
XS Rating Curve= 0 ,0
Exp/Cntr=0.3,0.1

Type RM Length L Ch R = 1 ,458.3   ,113.6,117.7,97.6
XS GIS Cut Line= 4
     1982441.937      436055.628     1982531.341      436076.343
     1982729.775      435983.668     1982784.289      435872.458
#Sta/Elev= 30
       0 1295.38     9.2 1291.75    18.4 1288.37    27.5 1285.25    36.7 1282.41
    45.9 1279.84    64.2 1275.42    82.6 1271.78    91.8 1270.24   111.7 1268.29
   131.6 1266.84   141.6 1266.29   191.3 1264.38   211.2 1263.08   221.2 1262.15
   231.1 1260.72   241.1 1257.44   244.5 1256.83     251 1255.66   259.5 1258.34
     261 1258.81     271 1263.42   280.9 1266.02   300.8 1268.86   310.8 1269.83
   329.8 1270.76   358.4 1271.71   367.9 1272.31     387 1274.05   434.6 1280.37
#Mann= 3 , 0 , 0
       0      .1       0   244.5    .045       0   259.5      .1       0
Bank Sta=244.5,259.5
XS Rating Curve= 0 ,0
Exp/Cntr=0.3,0.1

Type RM Length L Ch R = 1 ,340.7   ,344.7,45.8,46.5
XS GIS Cut Line= 4
     1982680.428      436115.774     1982715.271      436120.949
     1982739.764       436107.84     1982746.129      436036.003
#Sta/Elev= 18
       0 1226.75     8.8 1222.19    17.6 1217.34    26.4  1212.2    35.2 1207.71
    42.9 1206.39    44.5 1206.11    53.8 1206.46    57.9 1206.88      63  1207.4
      72 1208.93      81 1210.39      90 1212.54    99.1 1217.07   108.1 1224.22
   117.1 1232.41   126.1 1239.93   135.1 1246.51
#Mann= 3 , 0 , 0
       0      .1       0    42.9    .045       0    57.9      .1       0
Bank Sta=42.9,57.9
XS Rating Curve= 0 ,0
Exp/Cntr=0.3,0.1

Type RM Length L Ch R = 1 ,295.1   ,3658.2,40.3,36.5
XS GIS Cut Line= 4
     1982719.813      436164.071     1982728.092      436165.911
     1982754.311      436149.812      1982756.61      436125.894
#Sta/Elev= 11
       0  1204.1     8.5 1200.27    16.2 1198.43    17.6 1198.37    23.9  1198.1
    31.6 1198.63    32.6 1198.76    39.2 1199.61    47.3 1201.15    55.3 1202.56
    63.3 1203.85
#Mann= 3 , 0 , 0
       0      .1       0    17.6    .045       0    32.6      .1       0
Bank Sta=17.6,32.6
XS Rating Curve= 0 ,0
Exp/Cntr=0.3,0.1

Type RM Length L Ch R = 1 ,254.4   ,68.4,69.7,80.4
XS GIS Cut Line= 4
     1982704.232      436203.053     1982744.958      436201.863
     1982761.153      436191.324     1982769.777      436148.202
#Sta/Elev= 15
       0 1207.28     8.2 1204.09    16.3 1200.78    24.4 1197.44    32.6 1194.18
    40.7 1191.63    43.9 1191.38    50.4 1190.86    58.9 1191.41    60.1 1191.49
    68.9 1193.25    77.7    1195    86.4 1196.65    95.2 1198.09     104 1199.37
#Mann= 3 , 0 , 0
       0      .1       0    43.9    .045       0    58.9      .1       0
Bank Sta=43.9,58.9
XS Rating Curve= 0 ,0
Exp/Cntr=0.3,0.1

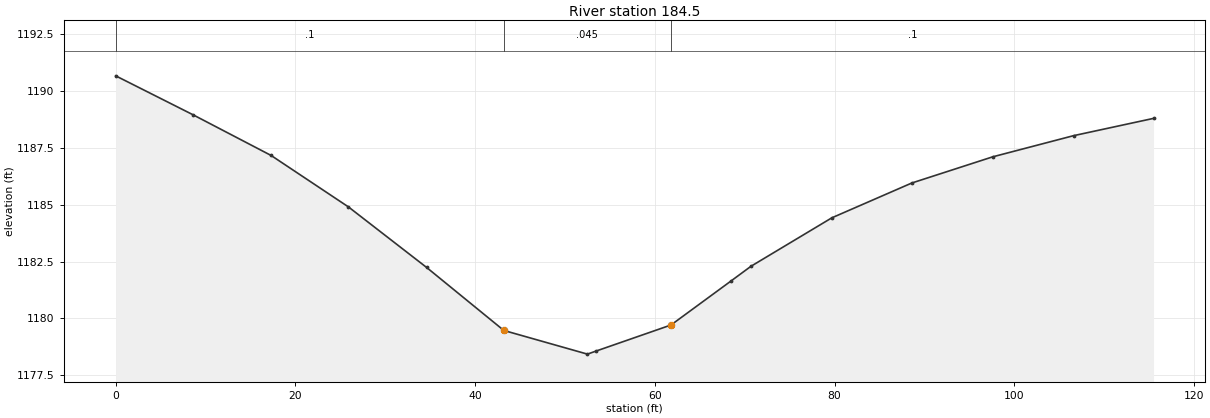
Type RM Length L Ch R = 1 ,184.5   ,189.7,184.6,197.1
XS GIS Cut Line= 4
      1982729.07      436257.214     1982771.727      436264.198
     1982788.559      436256.452     1982816.694      436210.643
#Sta/Elev= 16
       0 1190.66     8.6 1188.95    17.3 1187.16    25.9  1184.9    34.6 1182.24
    43.2 1179.47    52.5 1178.43    53.5 1178.57    61.8 1179.71    68.5 1181.65
    70.7 1182.29    79.7 1184.42    88.6 1185.95    97.6  1187.1   106.6 1188.03
   115.5 1188.79
#Mann= 3 , 0 , 0
       0      .1       0    43.2    .045       0    61.8      .1       0
Bank Sta=43.2,61.8
XS Rating Curve= 0 ,0
Exp/Cntr=0.3,0.1

Chan Stop Cuts=-1
Use User Specified Reach Order=0
Composite Channel Slope=5